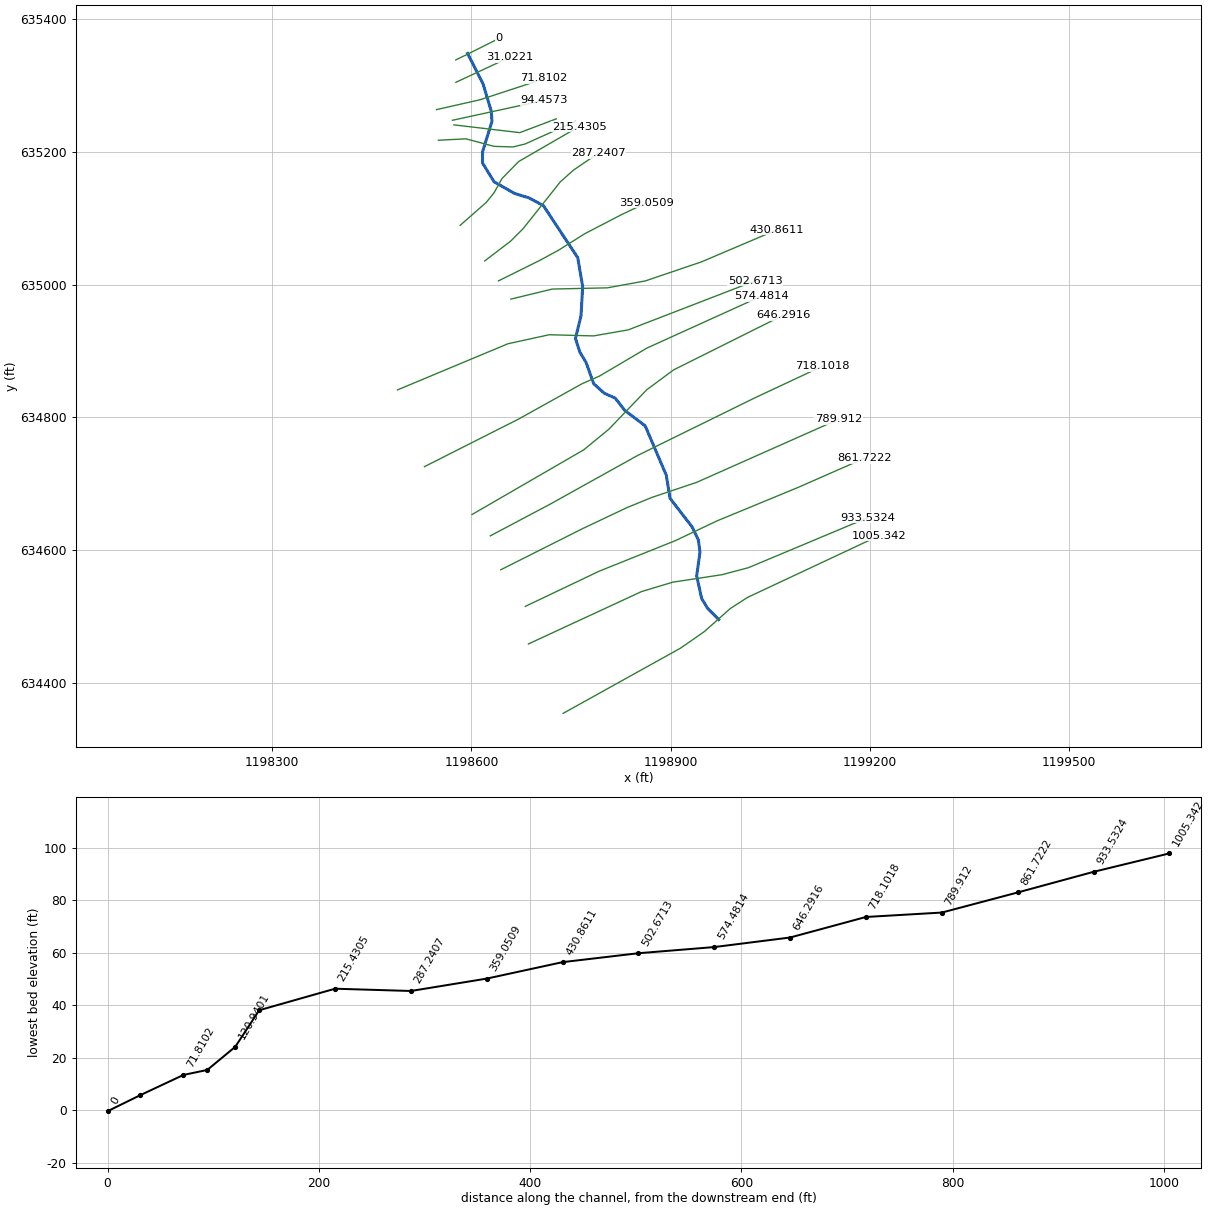
--- 502_ras.prj (project) ---

Proj Title=502
Current Plan=p01
Default Exp/Contr=0.3,0.1
English Units
Geom File=g01
Flow File=f01
Plan File=p01
Y Axis Title=Elevation
X Axis Title(PF)=Main Channel Distance
X Axis Title(XS)=Station
BEGIN DESCRIPTION:
RFD model 502 exported to HEC-RAS
END DESCRIPTION:

--- 502_ras.p01 (plan) ---

Plan Title=Plan 01
Program Version=4.10
Short Identifier=Plan 01
Geom File=g01
Flow File=f01
Subcritical Flow
Calc Critical at every XS
Secant Critical Depth

--- 502_ras.f01 (steady flow) ---

Flow Title=Flow 01
Program Version=5.01
Number of Profiles= 5
Profile Names=10yr,25yr,50yr,100yr,500yr
River Rch & RM=502,18,1005.342
  485.65   599.6  720.42  795.63  975.56
River Rch & RM=502,18,861.7222
  492.36   609.1  732.18  810.25  996.08
River Rch & RM=502,18,718.1018
  495.96  614.21   738.5  818.13 1007.15
River Rch & RM=502,18,574.4814
  502.46  623.45  749.93   832.4 1027.25
River Rch & RM=502,18,430.8611
  540.07  677.22  816.56  916.08  1146.1
River Rch & RM=502,18,287.2407
  545.27  684.69  825.84   927.8 1162.89
River Rch & RM=502,18,120.9401
  547.33  687.66  829.52  932.46 1169.55
Boundary for River Rch & Prof#=502,18,1
Up Type= 0
Dn Type= 2
Boundary for River Rch & Prof#=502,18,2
Up Type= 0
Dn Type= 2
Boundary for River Rch & Prof#=502,18,2
Up Type= 0
Dn Type= 2
Boundary for River Rch & Prof#=502,18,2
Up Type= 0
Dn Type= 2
Boundary for River Rch & Prof#=502,18,2
Up Type= 0
Dn Type= 2

--- 502_ras.g01 (geometry) ---

Geom Title=502
Program Version=4.10

River Reach=502,18
Reach XY= 30
1198972.49683785634495.4680459531198955.83017658 634512.13470817
1198946.66351304634527.1347039611198939.16351624634561.301360731
1198944.16351578634597.1346832671198941.66351706634615.468011232
1198932.49685365634634.634672461 1198899.1635314634677.967993891
1198893.33020081634712.9679836841198861.66354561634787.134629236
1198830.83022207634810.467956563 1198816.6635601634828.801284826
1198799.99689855634836.301283116 1198784.1635703634850.467946015
1198772.49690802634882.9679367111198763.33024449634897.967932521
1198756.66358038634918.8012598881198764.99691224634952.967916138
1198767.49691281634997.1345696061198759.99691627 635040.46789033
 1198708.3302671635118.8012019061198686.66360714635130.467865774
1198664.99694707635137.1345310791198634.16362334635154.634526737
1198616.66362933635182.9678522091198616.66362981635199.634513887
1198630.83029361635245.4678332421198629.99696096635260.467828801
1198617.49696585 635302.134483481198594.16364072635347.967803886

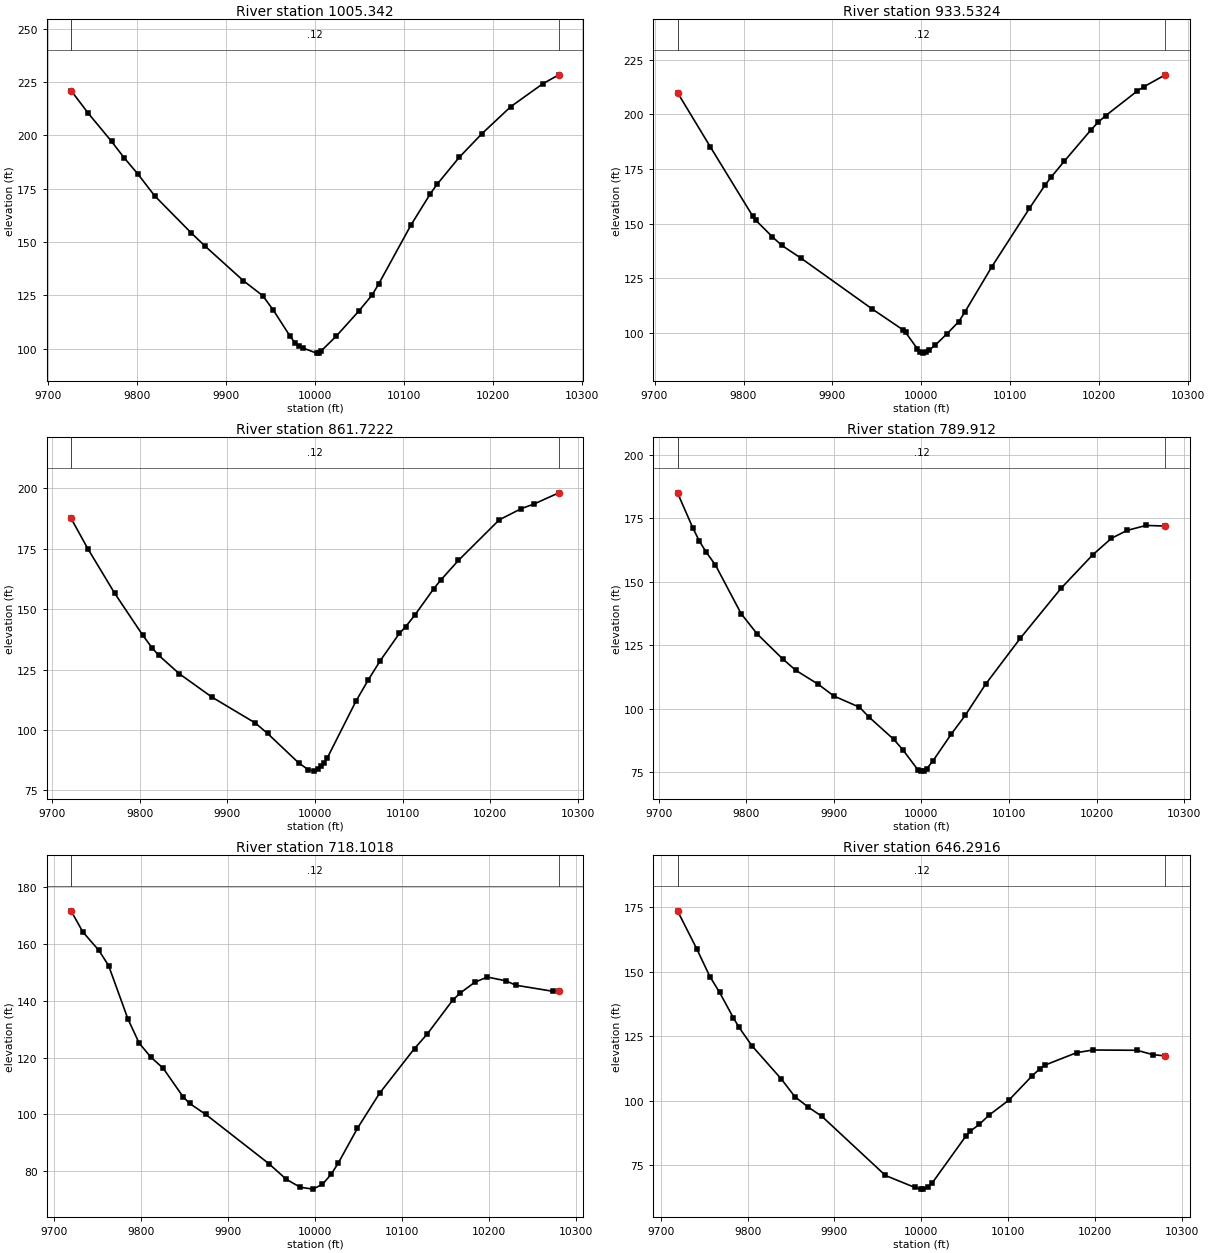
Type RM Length L Ch R = 1 ,1005.342,71.810100,71.810100,71.810100
XS GIS Cut Line= 6
 1198738.0265403634354.2080222281198914.95654483634452.499674716
1198950.38337908634477.1153568671198989.66335685634511.977028424
1199015.73184042634528.8248197491199214.27950866634621.942381693
#Sta/Elev= 30
9725.772220.95859745.163210.27949771.275197.14839785.367189.49229801.116181.7283
9819.768171.6254  9860.8154.26859875.983148.2211 9919.66131.78859941.261124.8199
9953.247118.01089972.233 105.6999977.791  102.639982.175101.1933 9986.56100.2788
10001.7897.88865 10004.298.0694410006.7598.8163410023.86105.801210049.25117.5619
10064.27125.131810071.61130.261610108.27158.154510129.93172.697710137.16176.9363
10162.43189.7488 10187.7200.717310220.19213.4155 10256.3224.178610274.22228.3319
#Mann= 3 , 0 , 0
9725.772    0.12       09725.772    0.12       010274.22    0.12       0
#XS Ineff= 2 , 0
       0                               0
Bank Sta=9725.772,10274.22
Exp/Cntr=0.3,0.1

Type RM Length L Ch R = 1 ,933.5324,71.810200,71.810200,71.810200
XS GIS Cut Line= 6
1198685.79265253634458.7556132641198856.04269768634537.588542964
1198903.19018691634551.7857485011198977.41956956634563.075724281
1199017.05159115 634573.582349951199197.20489549634649.057947405
#Sta/Elev= 30
9725.804209.89589762.787185.05179810.297153.51919813.952151.51289832.324144.0688
9842.932 140.124 9864.34134.35189944.763111.01579978.881 101.6269982.208100.3378
9995.51892.822739998.84691.3659810002.1990.86392 10005.591.3774910008.8192.25581
10015.4394.4659410028.6699.64463   10042 105.25410048.79109.582110079.36130.4423
10121.49 157.02610139.05167.678410146.07171.383210160.41178.444210190.74192.9089
 10198.9196.440310207.06199.329410242.82210.675810249.98212.5555 10274.2218.0331
#Mann= 3 , 0 , 0
9725.804    0.12       09725.804    0.12       0 10274.2    0.12       0
#XS Ineff= 2 , 0
       0                               0
Bank Sta=9725.804,10274.2
Exp/Cntr=0.3,0.1

Type RM Length L Ch R = 1 ,861.7222,71.810200,71.810200,71.810200
XS GIS Cut Line= 6
 1198681.1737262634515.3542667181198792.77550877634568.510845833
1198907.31219851634614.4199697891198969.77875061634644.050260015
1199091.72729082634694.4001840481199191.38671295634738.169486333
#Sta/Elev= 30
9721.549187.65429740.821174.9934 9771.34156.64319803.412139.25969814.314133.9046
9821.582130.96669845.163123.31059882.315113.66379931.799102.95089945.93798.58651
9981.63686.344339992.53383.58064    999983.0029610003.4383.8205610007.0685.10591
10010.6986.5289710014.3288.6052110046.78 111.91710060.98120.821210074.66128.7653
10096.48140.041510103.58142.776210114.22147.663810135.52158.440110143.43162.0015
10163.92  170.2610210.44187.019410235.53191.651310249.86193.534910278.48198.2056
#Mann= 3 , 0 , 0
9721.549    0.12       09721.549    0.12       010278.48    0.12       0
#XS Ineff= 2 , 0
       0                               0
Bank Sta=9721.549,10278.48
Exp/Cntr=0.3,0.1

Type RM Length L Ch R = 1 , 789.912,71.810200,71.810200,71.810200
XS GIS Cut Line= 6
1198644.19828465634570.4777922021198767.22934818634632.351768548
1198834.63556381634664.2272381211198871.70363961634679.410810079
1198939.32181297634702.1706361321199152.44333773634796.884694078
#Sta/Elev= 30
9721.535 185.0879739.152171.14029746.497166.04779753.842161.92649764.859156.5987
9794.238 137.401  9812.6129.39039841.979119.48249856.668115.08379882.103109.6207
9900.249104.92339929.282100.55589940.02396.704359968.38687.884499978.86883.74624
9996.06775.80131  9999.575.3409410002.9175.4421310006.3476.3664710013.1479.33997
10034.1789.9718610049.9797.2952210073.41109.665610112.91127.731610159.58147.4817
10195.48160.588410217.02167.162910234.97170.274910256.52172.227910278.47171.9852
#Mann= 3 , 0 , 0
9721.535    0.12       09721.535    0.12       010278.47    0.12       0
#XS Ineff= 2 , 0
       0                               0
Bank Sta=9721.535,10278.47
Exp/Cntr=0.3,0.1

Type RM Length L Ch R = 1 ,718.1018,71.810200,71.810200,71.810200
XS GIS Cut Line= 6
1198628.32558101634621.5052927781198718.20541576634669.099132802
1198849.57956553634742.2269775651198874.39799994634754.482999953
1199026.49748966634829.2319901551199128.17043211634876.845925222
#Sta/Elev= 30
9719.261171.76399732.757164.3526 9751.32157.79149762.457  152.479784.731 133.647
 9797.58125.16819810.718120.31219825.447116.2179 9848.15106.23829855.659103.8766
9874.43499.970839946.86882.663539967.10577.108879983.01974.331179997.65573.66111
10008.6175.3407210018.6878.9028810026.8982.8610810048.83 95.055410074.42107.4734
10114.63123.232810129.26128.3249 10158.5140.2421 10167.4142.817510183.95146.5809
10198.44148.420910220.18147.059910231.05145.546710274.52143.371510280.74143.5876
#Mann= 3 , 0 , 0
9719.261    0.12       09719.261    0.12       010280.74    0.12       0
#XS Ineff= 2 , 0
       0                               0
Bank Sta=9719.261,10280.74
Exp/Cntr=0.3,0.1

Type RM Length L Ch R = 1 ,646.2916,71.810200,71.810200,71.810200
XS GIS Cut Line= 6
1198600.94472194634653.6995754331198769.04358025634751.022104446
1198806.95964287634782.1427887731198864.01355538634841.557422159
 1198904.4069461634871.4419856051199070.05873938634954.105966844
#Sta/Elev= 30
9719.352173.66059741.673 158.804  9756.6148.19259767.796142.04689783.776132.1287
9790.187128.48789805.115121.32919838.647108.56749854.339101.67019869.90597.57087
9885.47294.045129958.66971.115859992.40466.497289999.64765.83212 10002.365.88032
10007.1966.5878710012.0868.0392910050.9586.2645410056.2188.2463610066.7190.94435
10077.8294.4706110101.03100.417210127.23109.637410136.32112.4721 10142.2113.8794
10178.65   118.710197.32119.733110248.06 119.62810266.17117.954810280.69117.4362
#Mann= 3 , 0 , 0
9719.352    0.12       09719.352    0.12       010280.69    0.12       0
#XS Ineff= 2 , 0
       0                               0
Bank Sta=9719.352,10280.69
Exp/Cntr=0.3,0.1

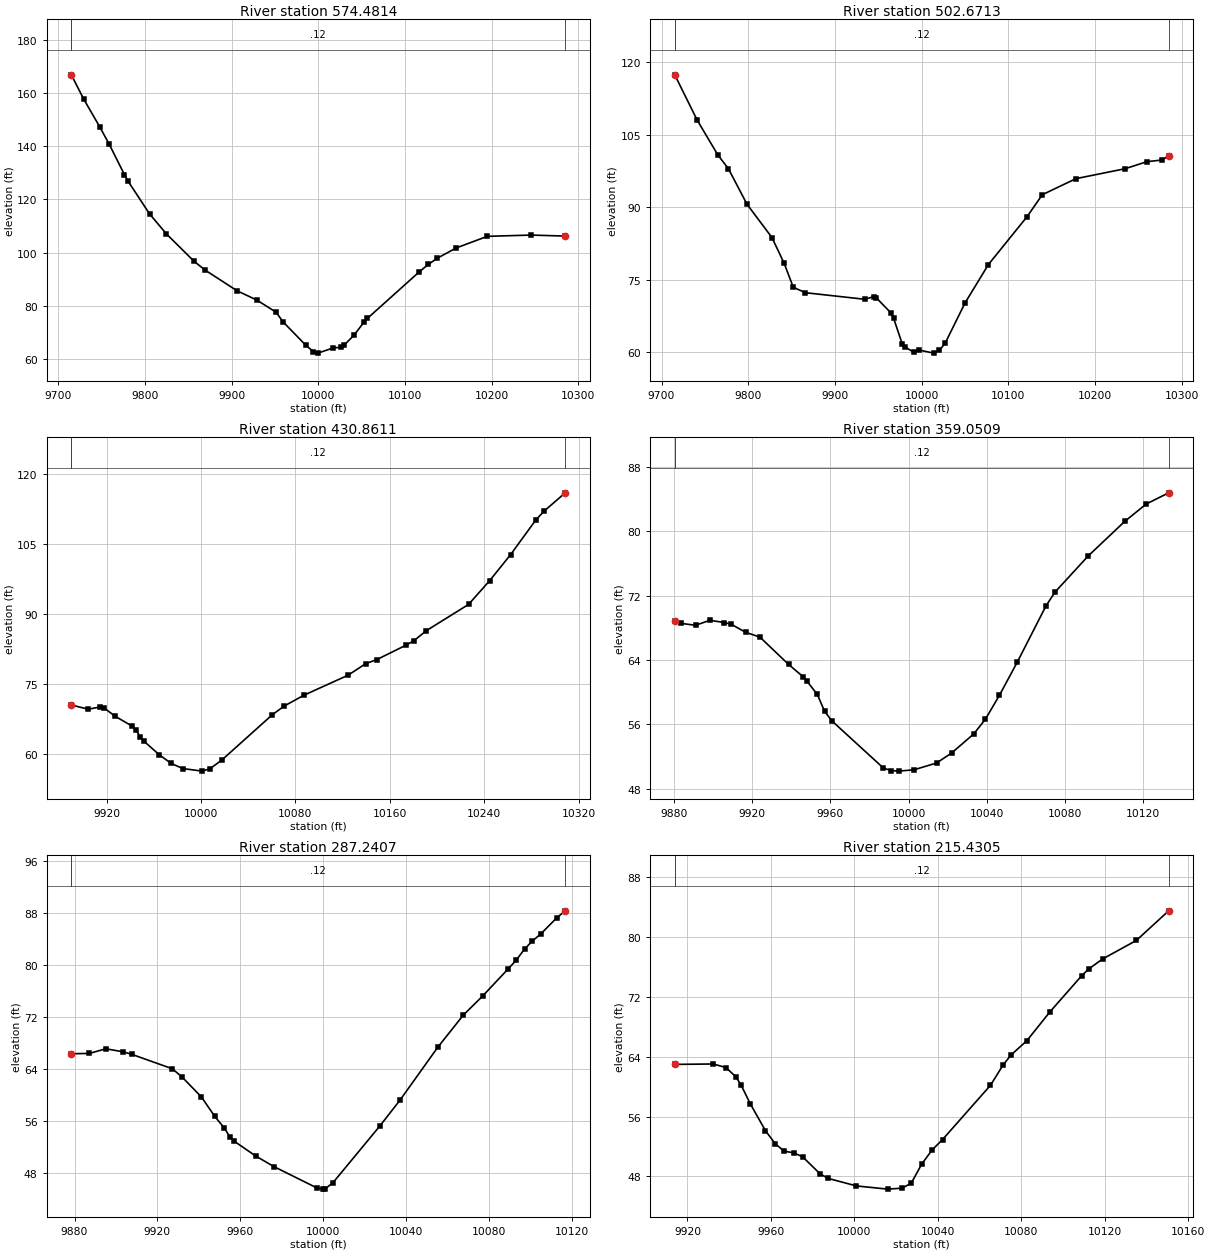
Type RM Length L Ch R = 1 ,574.4814,71.810100,71.810100,71.810100
XS GIS Cut Line= 6
1198529.20783753 634725.72560027 1198670.6282373634797.206366792
1198766.62953329634850.634774207 1198792.4156933 634861.91516751
1198864.38219749634904.3606163631199036.99450011634982.689245986
#Sta/Elev= 30
9715.185166.85159729.325157.77489747.706147.40759758.734140.82749776.312129.3627
9780.791126.74869805.404114.54039824.904107.00599856.31596.846659869.01793.50428
9906.46585.604459928.99482.162849951.52277.519739959.03174.055989985.23665.26556
9994.26162.753659999.58262.1887410017.2164.1618210025.66 64.362310029.52 65.1187
10041.1268.9049710052.7173.8538210056.5875.2386110115.7392.5502610126.6695.52512
10137.3597.8948910158.96 101.73510194.99106.114710245.75106.5885 10284.8 106.207
#Mann= 3 , 0 , 0
9715.185    0.12       09715.185    0.12       0 10284.8    0.12       0
#XS Ineff= 2 , 0
       0                               0
Bank Sta=9715.185,10284.8
Exp/Cntr=0.3,0.1

Type RM Length L Ch R = 1 ,502.6713,71.810200,71.810200,71.810200
XS GIS Cut Line= 6
 1198488.7085159634841.3500316551198654.93979402634910.792776375
1198717.01041959634924.3756457941198783.80521835634922.634418064
1198835.87950459634931.6281391371199027.64775772635005.714117647
#Sta/Elev= 30
9715.253117.41519741.085108.04889764.878100.8538 9777.0198.018839798.565 90.6365
9827.30583.758239841.41978.411149851.90273.47094 9865.8872.33754 9934.5170.97574
 9944.4971.523169947.81771.248359964.38268.191149967.66767.036629977.52161.76854
9980.80661.105579990.69160.035099997.28960.4655510013.8259.8384710020.3960.42328
10026.9561.8552110050.0870.2494210076.9478.1654410121.6188.0905810139.0692.60884
10177.8395.9324910234.7297.9967910259.6199.4425110276.8299.7846110284.78100.6484
#Mann= 3 , 0 , 0
9715.253    0.12       09715.253    0.12       010284.78    0.12       0
#XS Ineff= 2 , 0
       0                               0
Bank Sta=9715.253,10284.78
Exp/Cntr=0.3,0.1

Type RM Length L Ch R = 1 ,430.8611,71.810200,71.810200,71.810200
XS GIS Cut Line= 6
1198659.42562344634978.0432529041198721.72714513634993.164599152
1198804.62047348634995.0145775131198861.75998178635005.386910259
1198946.64416943635034.2192742111199060.10804859635082.472201922
#Sta/Elev= 30
9890.227 70.57349904.52569.677399914.73870.158129918.14269.906379927.23768.18051
9941.66566.068599944.99965.314779948.33263.751889951.66562.838089964.86359.91072
9974.73458.088479984.59356.9934510001.0256.4395310007.5856.9513210017.4358.75352
10060.3268.4657110070.3270.3221410087.1372.6565210124.7176.95849 10139.579.41278
10148.9280.2804310173.4283.3340210180.4284.3161110191.0286.4881910226.67 92.0784
 10244.597.1434310262.33102.736910283.72110.165510290.85 112.06810308.57115.9383
#Mann= 3 , 0 , 0
9890.227    0.12       09890.227    0.12       010308.57    0.12       0
#XS Ineff= 2 , 0
       0                               0
Bank Sta=9890.227,10308.57
Exp/Cntr=0.3,0.1

Type RM Length L Ch R = 1 ,359.0509,71.810200,71.810200,71.810200
XS GIS Cut Line= 6
1198640.58667205635005.4332176821198702.97630599635036.371692679
1198730.95193944635051.5849761121198770.48909384635076.403316333
1198826.72757774635105.613770168 1198863.9307089635123.235700154
#Sta/Elev= 30
9880.33368.860689883.62268.558919890.94668.32088 9898.2768.939899905.59468.66838
9909.25668.444289916.58167.450669923.90566.849439938.55363.454329945.87761.94582
9947.90261.381659953.26559.71788    995757.615129960.73456.421829987.10350.54748
9991.00450.243259994.906 50.167810002.7450.3333910014.2851.1790710021.9852.41945
10033.3254.7973110039.3156.6402510046.4359.5975210055.5163.6961410070.2970.73871
 10074.9 72.451910091.8876.9526310110.6281.2612210121.5183.4070710133.0484.80955
#Mann= 3 , 0 , 0
9880.333    0.12       09880.333    0.12       010133.04    0.12       0
#XS Ineff= 2 , 0
       0                               0
Bank Sta=9880.333,10133.04
Exp/Cntr=0.3,0.1

Type RM Length L Ch R = 1 ,287.2407,71.810200,71.810200,71.810200
XS GIS Cut Line= 6
1198619.92305328635035.4760676581198659.22760143635065.496348619
1198677.89513225635084.228129594 1198733.9634365 635154.75839641
1198753.91426851635172.4689337191198791.37233387   635197.996435
#Sta/Elev= 30
9878.48266.327559887.16566.370759895.07167.086849903.39166.631229907.64566.23227
9927.18464.006599931.89862.733419941.16259.680819947.59356.695439952.24154.87171
9955.00853.488619957.15352.81121 9967.4550.542239976.29348.90346 9996.8445.64372
10000.0245.44415   1000145.50821 10004.746.4410210027.17 55.1286   1003759.15567
10055.3867.3823110067.5972.2879210076.8575.20971   1008979.3388310093.0580.74377
10097.0982.4570710100.6983.6599210105.12 84.854210112.7187.3064110116.7488.36626
#Mann= 3 , 0 , 0
9878.482    0.12       09878.482    0.12       010116.74    0.12       0
#XS Ineff= 2 , 0
       0                               0
Bank Sta=9878.482,10116.74
Exp/Cntr=0.3,0.1

Type RM Length L Ch R = 1 ,215.4305,71.810100,71.810100,71.810100
XS GIS Cut Line= 6
1198583.00374029635089.1530829781198622.33431604635123.673694493
1198633.99050825635138.1030468581198646.20627816635159.824845493
1198671.12392393  635185.21123691198762.03390749635237.822353158
#Sta/Elev= 30
9913.92162.959319932.33163.013539938.48762.536319943.21561.294389945.65160.22579
9950.20857.653549957.39754.105479962.125 52.35059966.33251.379299971.01451.15015
9975.23150.619099983.66648.323949987.59247.73102   1000146.73659   1001646.31155
10022.8446.4391410027.24 47.092510032.2549.6456310037.2751.5421610042.2852.93501
10065.2160.1628210071.3262.8946310075.08 64.215310082.5966.1007110093.85 70.0092
10108.8774.7682510112.2975.6882610119.0477.0396810135.1579.5008610150.6283.45455
#Mann= 3 , 0 , 0
9913.921    0.12       09913.921    0.12       010150.62    0.12       0
#XS Ineff= 2 , 0
       0                               0
Bank Sta=9913.921,10150.62
Exp/Cntr=0.3,0.1

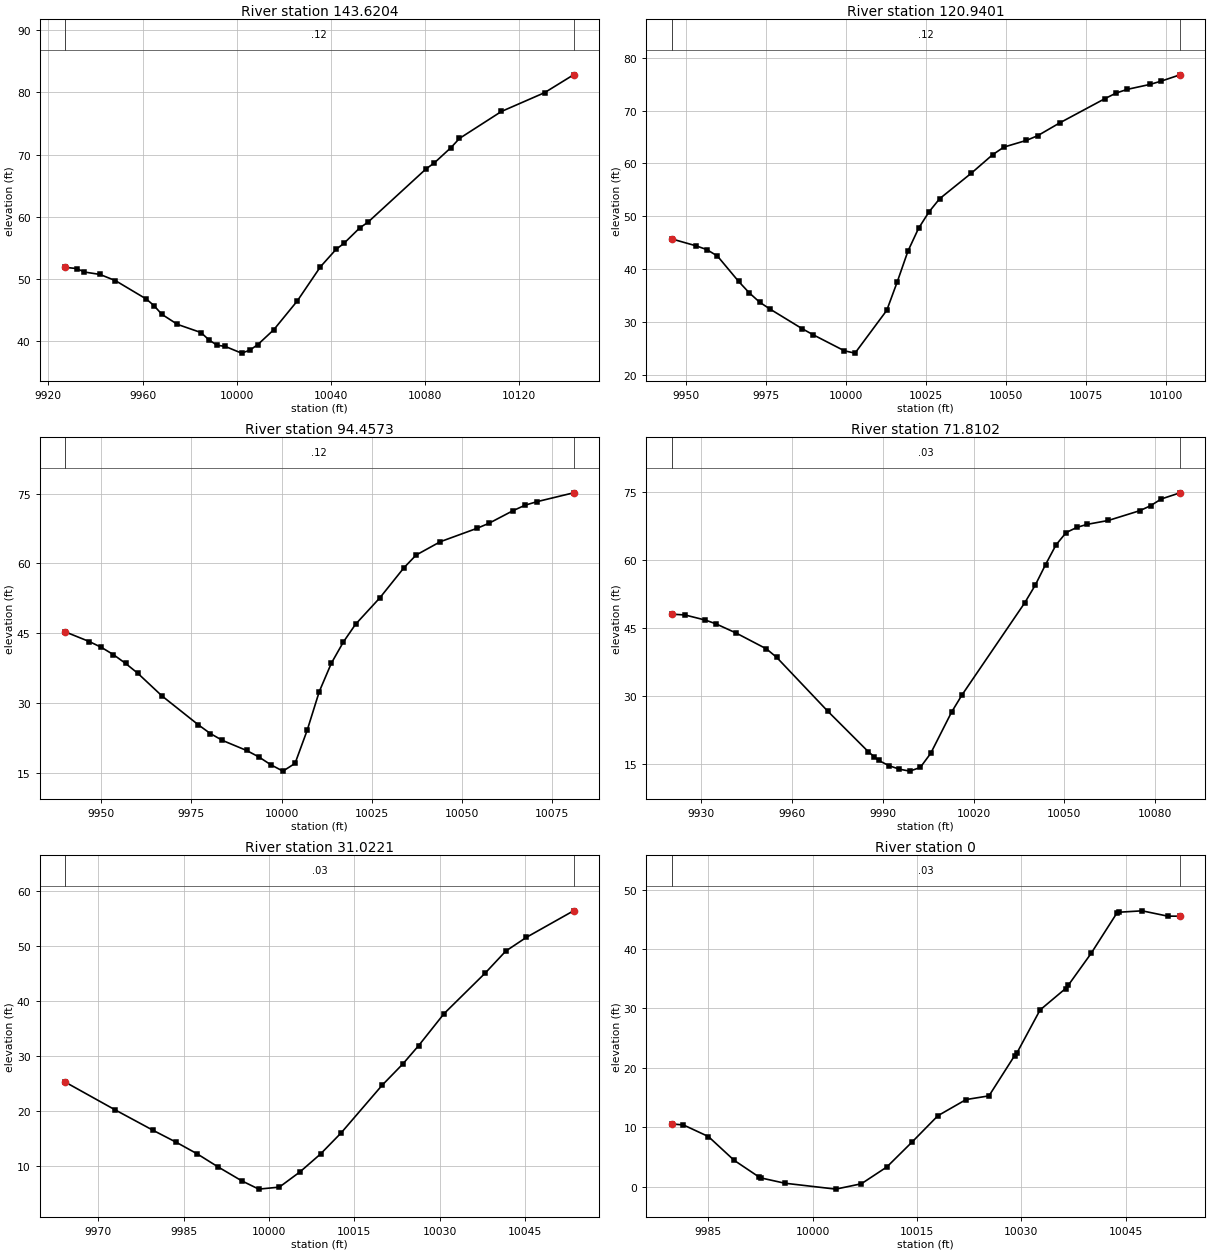
Type RM Length L Ch R = 1 ,143.6204,22.680300,22.680300,22.680300
XS GIS Cut Line= 6
1198550.16920079   635217.2477961198591.71919015635219.396270341
  1198633.976244635208.046343707 1198662.5592877 635207.16798572
1198680.80879485 635211.646069851198756.26643704635245.651498557
#Sta/Elev= 30
9927.13151.890499931.95151.703049935.25851.142349941.871 50.75529948.46949.75747
9961.59346.798819964.87445.733259968.155 44.35269974.80442.728229984.79341.41684
9988.15640.248649991.61639.378659995.07739.1885910002.0538.1085910005.5138.57257
10008.9739.4880710015.75 41.877910025.6946.4813810035.5551.9853810042.1554.76825
10045.5355.7507510052.2858.2426510055.6659.1204210080.3567.6921310083.9268.67439
10091.0471.1453810094.6172.6078610112.4376.9396110130.7579.9588410143.0682.82788
#Mann= 3 , 0 , 0
9927.131    0.12       09927.131    0.12       010143.06    0.12       0
#XS Ineff= 2 , 0
       0                               0
Bank Sta=9927.131,10143.06
Exp/Cntr=0.3,0.1

Type RM Length L Ch R = 1 ,120.9401,26.482800,26.482800,26.482800
XS GIS Cut Line= 3
1198573.56727251635240.4111860251198672.77034059635228.714754388
1198727.78688923635249.508410603
#Sta/Elev= 30
9945.53845.750079953.22244.428079956.52543.725739959.829  42.5079966.43637.71724
 9969.74 35.56859973.04333.771359976.34732.453179986.25728.791239989.56127.68431
9999.472 24.601810002.7824.1683210012.6932.2537410015.99 37.676110019.2943.41928
 10022.647.73012 10025.950.87401 10029.253.3424210039.1158.1747210045.7461.65373
10049.2563.0924210056.26 64.356410059.7765.2371810066.7867.6983110080.81 72.2521
10084.3273.3115110087.8374.0093910094.8474.9318910098.3575.5549510104.2476.74902
#Mann= 3 , 0 , 0
9945.538    0.12       09945.538    0.12       010104.24    0.12       0
#XS Ineff= 2 , 0
       0                               0
Bank Sta=9945.538,10104.24
Exp/Cntr=0.3,0.1

Type RM Length L Ch R = 1 , 94.4573,22.647100,22.647100,22.647100
XS GIS Cut Line= 2
1198571.40126669635247.3424047381198709.15923887635277.233285487
#Sta/Elev= 30
9940.01845.277189946.68543.196519950.04241.947999953.39940.373959956.75738.49716
9960.11436.396449966.82831.52411  9976.925.322439980.25723.433049983.61421.95419
9990.32819.784839993.68518.414459997.04316.71714 10000.415.3506410003.7617.02089
10007.1124.1099610010.4732.4383410013.8338.5538310017.1943.1368710020.54 46.9135
10027.2652.5768510033.9759.0665210037.3361.7793410044.0464.6452710054.1167.49466
10057.4768.5829610064.1971.3101810067.5472.49057 10070.973.2608210080.98 75.1501
#Mann= 3 , 0 , 0
9940.018    0.12       09940.018    0.12       010080.98    0.12       0
#XS Ineff= 2 , 0
       0                               0
Bank Sta=9940.018,10080.98
Exp/Cntr=0.3,0.1

Type RM Length L Ch R = 1 , 71.8102,40.788100,40.788100,40.788100
XS GIS Cut Line= 6
1198547.34539189635263.370008013 1198611.6499204635277.925412031
1198623.98056786635281.749520326 1198625.8560654635282.444148985
1198693.68679495635304.7262653651198708.33509088635310.716674319
#Sta/Elev= 30
9920.15948.012459924.59347.828279931.32146.699469934.68445.909849941.41243.86996
9951.50440.358039954.86738.497099971.68726.685849985.14217.72624 9987.1316.58511
9988.55715.798059991.99214.634919995.42713.862449998.86213.4302810002.3414.23327
10005.7917.33912 10012.726.4316610016.15 30.219310036.8750.4906310040.3354.35592
10043.7858.9422510047.2363.2677310050.5865.9848710054.1467.1317910057.5967.80238
 10064.568.6456910074.9370.8051310078.4771.8858710082.01 73.378610088.2274.73847
#Mann= 3 , 0 , 0
9920.159    0.03       09920.159    0.03       010088.22    0.03       0
#XS Ineff= 2 , 0
       0                               0
Bank Sta=9920.159,10088.22
Exp/Cntr=0.3,0.1

Type RM Length L Ch R = 1 , 31.0221,31.022100,31.022100,31.022100
XS GIS Cut Line= 2
1198576.59968075635304.5249592511198657.60829961635342.213461071
#Sta/Elev= 20
9964.16225.227199972.85220.217499979.61116.442099983.70714.251929987.32612.17634
9990.9449.8317729995.1677.2560519998.1825.730599 10001.8 6.0957210005.428.862654
10009.0412.1291710012.6615.9718210019.8924.6811310023.5128.5337510026.2831.86635
10030.7537.6946310037.9945.09269 10041.649.0920210045.2251.5913710053.5156.42513
#Mann= 3 , 0 , 0
9964.162    0.03       09964.162    0.03       010053.51    0.03       0
#XS Ineff= 2 , 0
       0                               0
Bank Sta=9964.162,10053.51
Exp/Cntr=0.3,0.1

Type RM Length L Ch R = 1 ,       0,0.000000,0.000000,0.000000
XS GIS Cut Line= 4
1198576.38718989635338.287608117  1198593.751876635346.614862725
1198595.51658189635347.5560391551198641.83743108635370.722695409
#Sta/Elev= 25
9979.74210.574049981.43810.400659985.019 8.451569988.716 4.454789992.3541.598065
9992.6061.4793249995.9930.60036610003.33-0.39566   100070.50561510010.67 3.33971
10014.347.590626   1001811.9567110022.0514.6755510025.3415.2970710029.0122.04022
10029.3922.5893410032.68 29.747910036.3533.3577510036.72 33.882610040.0139.25562
10043.68 45.983510044.06 46.198410047.3546.4295810051.0245.5365210052.7945.52722
#Mann= 3 , 0 , 0
9979.742    0.03       09979.742    0.03       010052.79    0.03       0
#XS Ineff= 2 , 0
       0                               0
Bank Sta=9979.742,10052.79
Exp/Cntr=0.3,0.1